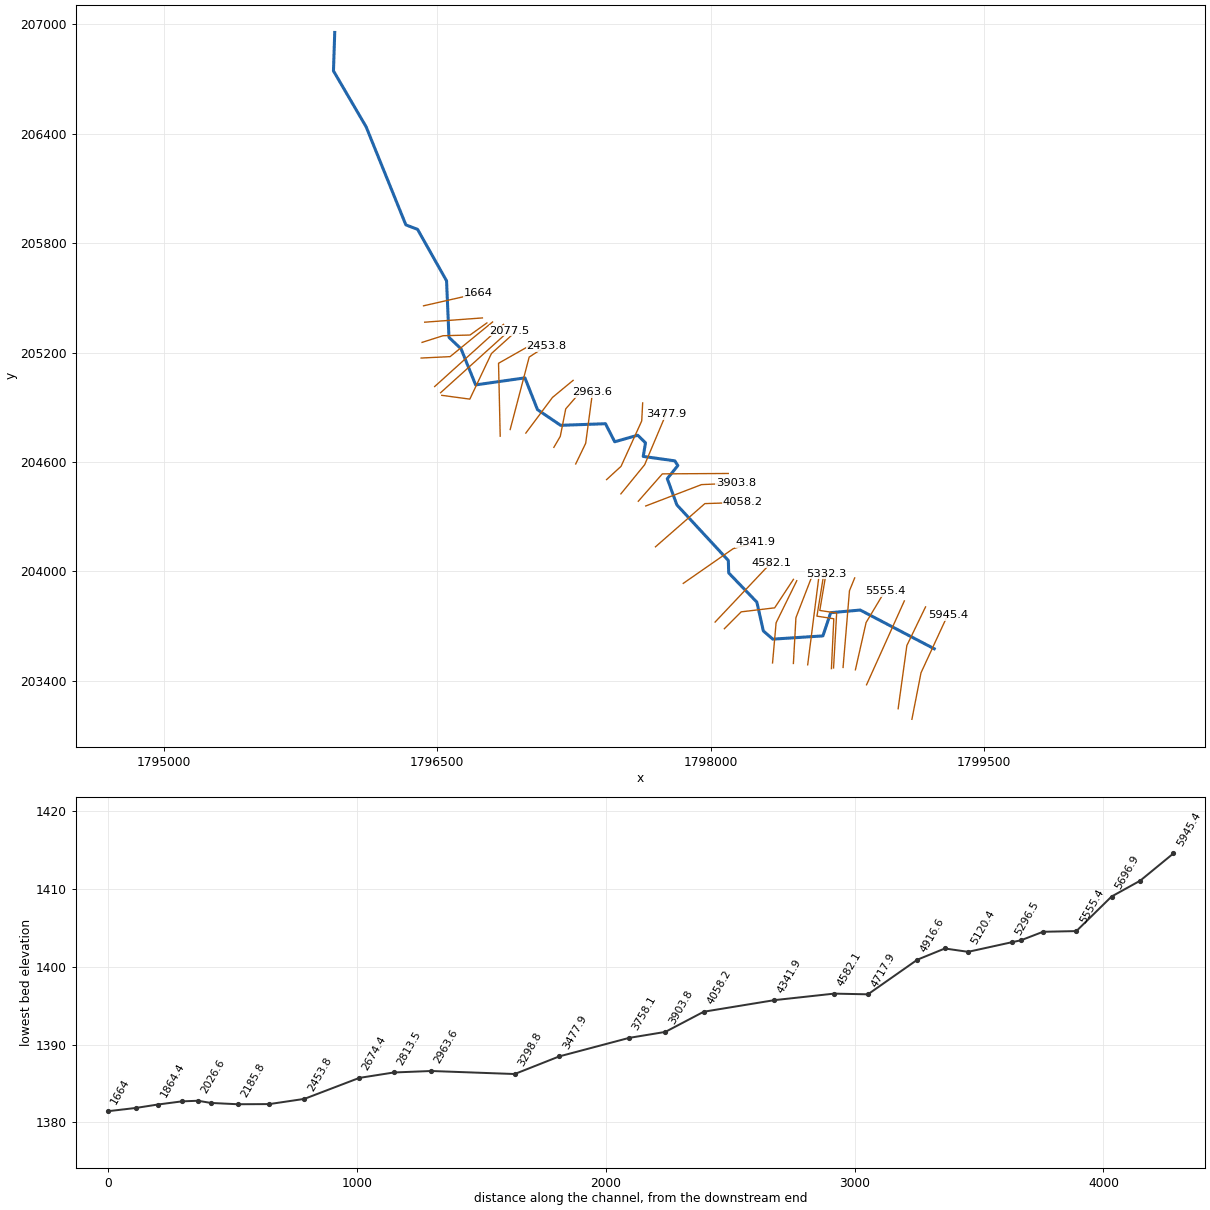
--- LKSHOALSRN.prj (project) ---

Proj Title=LKSHOALSRN
Current Plan=p01
Geom File=g01
Flow File=f01
Plan File=p01
DSS Export Rating Curves=0
DSS Export Rating Curve Sorted=0
DSS Export Volume Flow Curves=0
DXF OffsetX=0
DXF OffsetY=0
DXF ScaleX=0
DXF ScaleY=0

--- LKSHOALSRN.p01 (plan) ---

Plan Title=Floodplain
Program Version=4.00
Geom File=g01
Flow File=f01
K Sum by GR=0
Std Step Tol=0.01
Critical Tol=0.01
Num of Std Step Trials=20
Max Error Tol=0.3
Flow Tol Ratio=0.001
Split Flow NTrial=30
Split Flow Tol=0.02
Split Flow Ratio=0.02
Log Output Level=0
Friction Slope Method=1
Unsteady Friction Slope Method=2
Unsteady Bridges Friction Slope Method=1
Global Log Level=0
CheckData=False
Run HTab=0
Run UNet=0
Run PostProcess=0
UNET Theta=0
UNET Theta Warmup=0
UNET ZTol=0
UNET ZSATol=0
UNET MxIter=0
UNET MaxInSteps=0
UNET DtIC=0
UNET DtMin=0
UNET MaxCRTS=0
UNET WFStab=0
UNET SFStab=0
UNET WFX=0
UNET SFX=0
UNET DSS MLevel=0
UNET DZMax Abort=0
UNET Convert EG Bridges=0
UNET Use Existing IB Tables=0
UNET Froude Limit=0
UNET Froude Power=0
Write IC File=0
Echo Input=False
Echo Output=False
Write Detailed=0

--- LKSHOALSRN.f01 (steady flow) ---

Flow Title=NFF Regression Equation
Program Version=4.00
Number of Profiles=1
Profile Names=P100yr
River Rch & RM=LKSHOALSRN,Main      ,5945.4
543.2134
River Rch & RM=LKSHOALSRN,Main      ,4717.9
572.9040
River Rch & RM=LKSHOALSRN,Main      ,2963.6
616.5679
River Rch & RM=LKSHOALSRN,Main      ,582
657.2905
River Rch & RM=LKSHOALSRN,Main      ,294
659.6661
Boundary for River Rch & Prof#=LKSHOALSRN,Main      ,1
Up Type=0
Dn Type=3
Dn Slope=0.019177

--- LKSHOALSRN.g01 (geometry) ---

Geom Title=USGS 10m DEM
Program Version=4.10

River Reach=LKSHOALSRN      ,Main
Reach XY= 30
     1799226.461      203575.939     1798820.776      203788.215
     1798658.796      203773.921     1798615.943      203646.526
     1798341.215      203628.766     1798289.456      203673.654
     1798253.832      203831.651     1798099.398      203991.888
     1798097.438      204059.975      1797815.21      204364.894
      1797762.56      204508.669      1797820.61      204580.895
     1797803.735      204606.545       1797630.7      204630.782
     1797643.084      204705.096     1797600.558      204746.946
     1797474.332      204711.171     1797423.675      204810.083
     1797177.698      204801.286     1797050.823      204887.367
     1796981.949      205061.519     1796711.566       205023.03
     1796631.749      205220.539     1796565.342      205283.733
     1796552.148      205593.803     1796393.247      205875.816
     1796328.899      205900.631     1796111.009      206438.484
     1795931.948      206744.959     1795938.905      206955.869

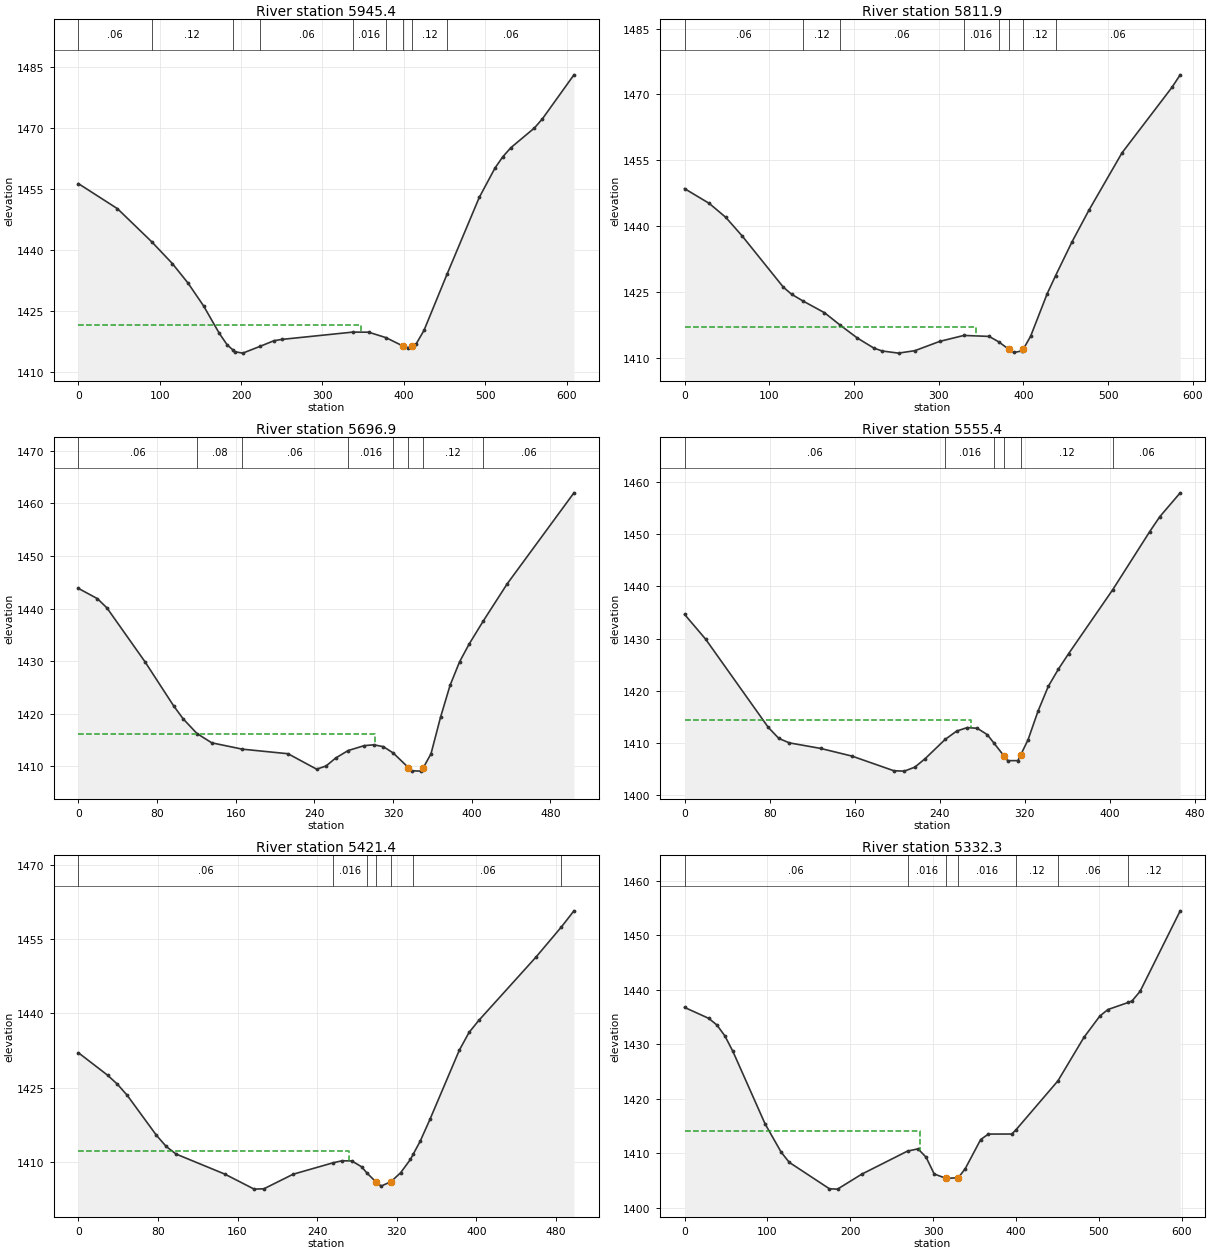
Type RM Length L Ch R = 1 ,5945.4  ,133.8,133.5,133
XS GIS Cut Line= 3
     1799104.163      203189.338     1799154.059      203444.354
      1799300.64      203761.353
#Sta/Elev= 30
       0 1456.34    48.1 1450.16   90.141442.025   115.5 1436.66   134.7 1431.88
     154 1426.21   173.2 1419.49   182.9 1416.65  189.661415.446   192.5 1414.94
   202.1  1414.6  223.071416.247   240.6 1417.67   250.2 1417.98  337.48 1419.78
   356.9 1419.75  378.081418.412  398.671416.381   405.4 1415.91  410.441416.393
   415.1 1416.84   424.8 1420.19  453.291434.109   492.7 1452.92   512.1 1460.18
   521.8 1462.97   531.5 1465.16   560.6 1470.04   570.3 1472.27   609.1 1483.11
#Mann= 9 ,-1 , 0
       0     .06       0   90.14     .12       0  189.66     .08       0
  223.07     .06       0  337.48    .016       0  378.08     .12       0
  398.67    .045       0  410.44     .12       0  453.29     .06       0
#XS Ineff= 2 , 0
          347.47 1421.49
Permanent Ineff=
       F       F
Bank Sta=398.67,410.44
XS Rating Curve= 0 ,0
Exp/Cntr=0.3,0.1

Type RM Length L Ch R = 1 ,5811.9  ,114.5,115,115.7
XS GIS Cut Line= 3
     1799028.642      203247.064     1799076.344       203593.53
     1799178.865      203805.496
#Sta/Elev= 30
       0 1448.56    29.1  1445.2    48.6 1442.03      68 1437.78   116.6 1426.12
   126.3 1424.51  139.811422.967   165.2  1420.3   183.41417.517     204 1414.53
   223.4 1412.25   233.2 1411.58   252.6 1411.09     272 1411.65   301.2 1413.76
   329.81415.121   359.6  1414.9  371.041413.649  382.711411.983     389 1411.24
   398.8 1411.61  399.951412.002   408.6 1414.94   428.2 1424.65  438.071428.738
   457.6 1436.49   477.3  1443.6   516.5 1456.71   575.4 1471.61   585.2 1474.48
#Mann= 8 ,-1 , 0
       0     .06       0  139.81     .12       0   183.4     .06       0
   329.8    .016       0  371.04     .12       0  382.71    .045       0
  399.95     .12       0  438.07     .06       0
#XS Ineff= 2 , 0
          344.27 1416.98
Permanent Ineff=
       F       F
Bank Sta=382.71,399.95
XS Rating Curve= 0 ,0
Exp/Cntr=0.3,0.1

Type RM Length L Ch R = 1 ,5696.9  ,143.8,141.5,138.7
XS GIS Cut Line= 2
     1798855.465      203378.574     1799062.497       203838.21
#Sta/Elev= 30
       0 1443.84    19.4 1441.88    29.1 1440.12    67.9 1429.84    96.9 1421.49
   106.6 1419.01   120.71416.202   135.7 1414.44   166.71413.233   213.3 1412.36
   242.4 1409.42     252 1410.03   261.8 1411.55  274.331412.961   290.8  1413.9
   300.5 1414.06   310.2 1413.71  320.241412.508   335.7 1409.73   339.3 1409.11
     349 1409.05   350.7 1409.63   358.7 1412.35   368.4  1419.3   378.1 1425.38
   387.8 1429.87   397.5 1433.24  412.091437.692   436.2  1444.7   504.1 1462.02
#Mann= 8 ,-1 , 0
       0     .06       0   120.7     .08       0   166.7     .06       0
  274.33    .016       0  320.24     .12       0   335.7    .045       0
   350.7     .12       0  412.09     .06       0
#XS Ineff= 2 , 0
          302.17  1416.2
Permanent Ineff=
       F       F
Bank Sta=335.7,350.7
XS Rating Curve= 0 ,0
Exp/Cntr=0.3,0.1

Type RM Length L Ch R = 1 ,5555.4  ,122.9,134,144.1
XS GIS Cut Line= 3
     1798794.267      203460.605     1798852.861       203719.72
     1798955.726      203891.595
#Sta/Elev= 30
       0 1434.63    19.7 1429.91    78.7 1412.99    88.6 1410.87    98.4 1410.02
   127.9 1408.95   157.4 1407.48   196.8 1404.67   206.6  1404.6   216.5 1405.36
   226.3 1407.01  244.961410.667   255.8 1412.27   265.7 1412.94   275.2 1412.81
   284.7 1411.58  290.891409.974   300.11407.578   303.8 1406.61   313.4 1406.61
  315.991407.694   322.9 1410.58   332.4 1416.13     342 1420.85   351.5 1424.15
     361 1427.08  402.581439.365   437.4 1450.51   446.9 1453.37     466 1457.92
#Mann= 6 ,-1 , 0
       0     .06       0  244.96    .016       0  290.89     .12       0
   300.1    .045       0  315.99     .12       0  402.58     .06       0
#XS Ineff= 2 , 0
          269.35 1414.49
Permanent Ineff=
       F       F
Bank Sta=300.1,315.99
XS Rating Curve= 0 ,0
Exp/Cntr=0.3,0.1

Type RM Length L Ch R = 1 ,5421.4  ,59.6,89.1,126.4
XS GIS Cut Line= 3
     1798726.559      203473.626     1798761.715      203894.199
     1798790.361      203964.512
#Sta/Elev= 30
       0 1432.04    29.4  1427.5    39.3 1425.67    49.1 1423.45    78.5 1415.37
    88.3 1413.12    98.2 1411.59   147.2 1407.54   176.7 1404.51   186.5 1404.58
   215.9 1407.52  256.031409.827     265 1410.23   274.8  1410.2   284.6 1409.02
  290.271407.701  298.791406.025   304.3 1405.13   314.1    1406   323.9 1407.83
   333.7 1410.51  336.711411.637   343.5 1414.18   353.3 1418.58   382.8 1432.53
   392.6 1436.13   402.4 1438.55     460 1451.36  485.371457.406     498 1460.66
#Mann= 7 ,-1 , 0
       0     .06       0  256.03    .016       0  290.27     .12       0
  298.79    .045       0   314.1     .12       0  336.71     .06       0
  485.37     .12       0
#XS Ineff= 2 , 0
          272.45 1412.18
Permanent Ineff=
       F       F
Bank Sta=298.79,314.1
XS Rating Curve= 0 ,0
Exp/Cntr=0.3,0.1

Type RM Length L Ch R = 1 ,5332.3  ,28.5,35.7,33.5
XS GIS Cut Line= 4
     1798674.476      203471.022     1798691.403      203771.803
     1798598.955      203786.126     1798632.809      203986.647
#Sta/Elev= 30
       0 1436.75    29.2 1434.74    38.9 1433.54    48.6 1431.54    58.3 1428.69
    97.2 1415.38   116.6 1410.19   126.3 1408.33   174.9 1403.47   184.6 1403.41
   213.8 1406.15  269.071410.388   281.8  1410.8   291.5 1409.27   301.3 1406.19
  315.831405.371  330.46 1405.51   338.7 1407.15   357.4 1412.51   366.7 1413.51
   394.8 1413.52  399.871414.267  450.641423.279     482 1431.25   501.3 1435.18
     511 1436.36  535.711437.668   540.1 1437.94   549.8  1439.7   598.2 1454.47
#Mann= 7 ,-1 , 0
       0     .06       0  269.07    .016       0  315.83    .045       0
  330.46    .016       0  399.87     .12       0  450.64     .06       0
  535.71     .12       0
#XS Ineff= 2 , 0
          284.21 1413.99
Permanent Ineff=
       F       F
Bank Sta=315.83,330.46
XS Rating Curve= 0 ,0
Exp/Cntr=0.3,0.1

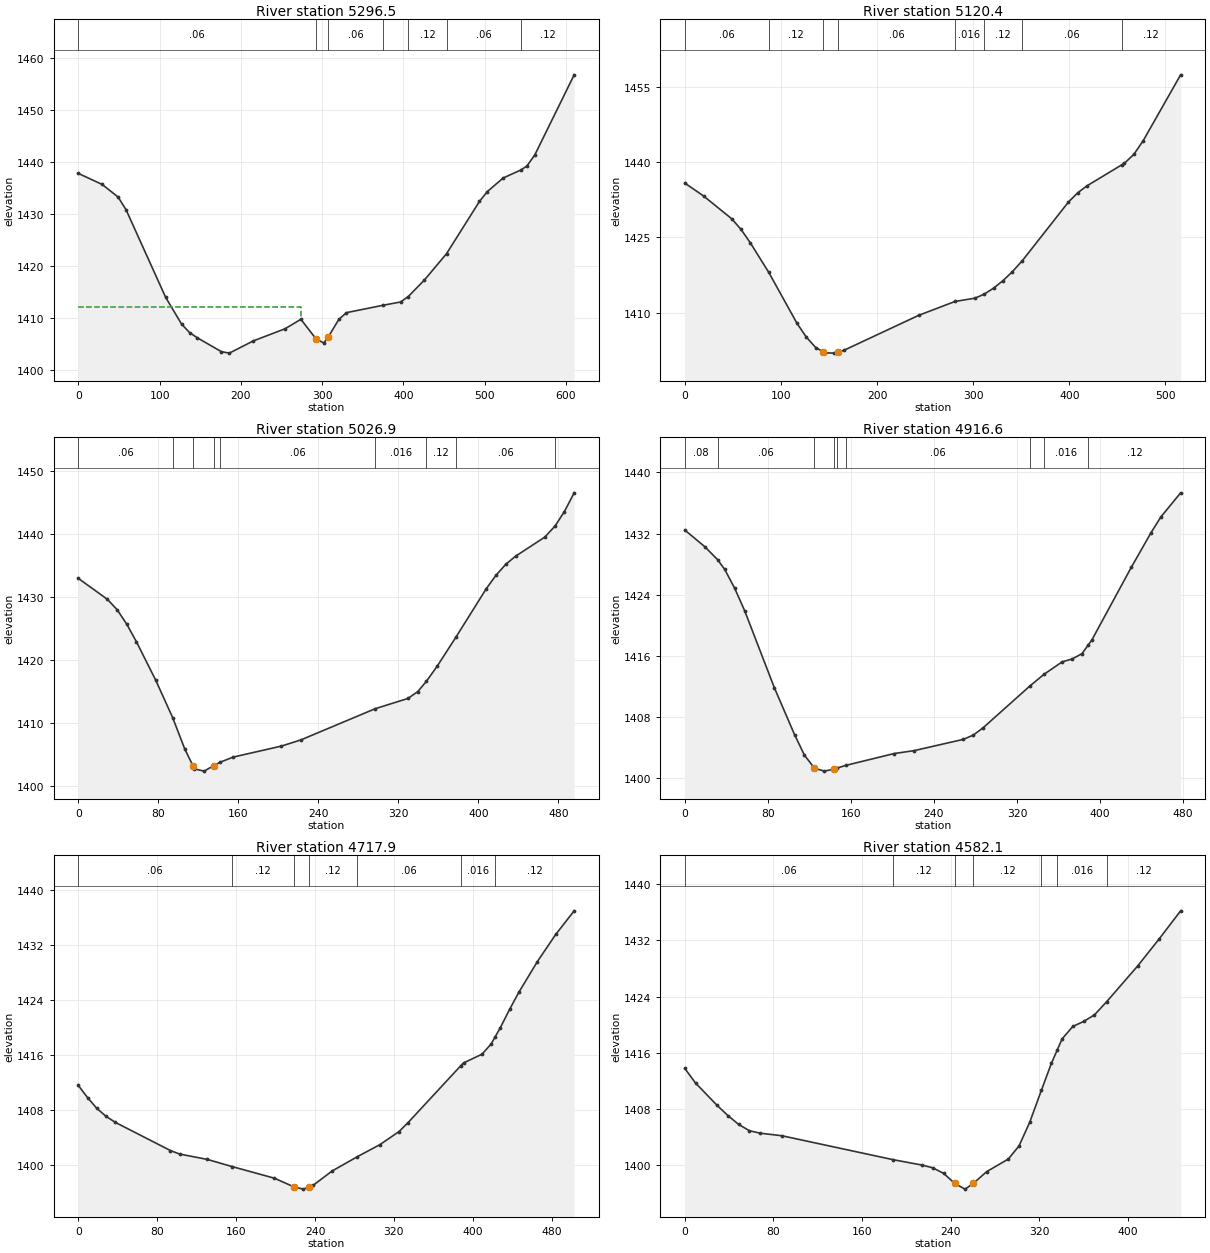
Type RM Length L Ch R = 1 ,5296.5  ,211.4,176.1,140.3
XS GIS Cut Line= 4
     1798662.757      203467.116     1798675.778      203740.553
      1798583.33      203754.876     1798622.392       203994.46
#Sta/Elev= 30
       0 1437.75    29.3 1435.63    48.9 1433.21    58.7 1430.76   107.5 1413.88
   127.1 1408.74   136.9 1407.12   146.6  1406.1     176 1403.45   185.8 1403.17
   215.1 1405.51   254.2 1407.85   273.8 1409.68   292.1 1405.98   301.8 1405.11
   307.1 1406.18   320.5 1409.66   329.9 1410.96  374.971412.382   396.4 1413.01
  405.951414.063   425.6 1417.21  453.021422.312   493.5 1432.36   503.2 1434.26
   522.7 1436.87  544.341438.401   551.8 1439.17   561.5 1441.28     610 1456.72
#Mann= 7 ,-1 , 0
       0     .06       0   292.1    .045       0   307.1     .06       0
  374.97    .016       0  405.95     .12       0  453.02     .06       0
  544.34     .12       0
#XS Ineff= 2 , 0
          273.79 1411.96
Permanent Ineff=
       F       F
Bank Sta=292.1,307.1
XS Rating Curve= 0 ,0
Exp/Cntr=0.3,0.1

Type RM Length L Ch R = 1 ,5120.4  ,91.8,93.4,95
XS GIS Cut Line= 2
     1798532.549      203487.949     1798597.653      203999.668
#Sta/Elev= 30
       0 1435.82    19.5 1433.25    48.7 1428.72    58.4 1426.61    68.1 1423.93
   87.41    1418   116.8 1407.84   126.5 1405.11   136.3 1403.02  143.971402.205
     146 1401.99   155.7 1401.93  159.741402.163   165.5 1402.49   243.3 1409.46
  281.061412.223   301.7 1412.88  310.891413.619   321.2 1414.87   330.9 1416.36
   340.6 1418.12  351.241420.379     399 1432.02   408.8 1433.89   418.5 1435.28
  454.681439.466   457.4 1439.78   467.2 1441.55   476.9 1444.28   515.8 1457.39
#Mann= 8 ,-1 , 0
       0     .06       0   87.41     .12       0  143.97    .045       0
  159.74     .06       0  281.06    .016       0  310.89     .12       0
  351.24     .06       0  454.68     .12       0
Bank Sta=143.97,159.74
XS Rating Curve= 0 ,0
Exp/Cntr=0.3,0.1

Type RM Length L Ch R = 1 ,5026.9  ,111.1,110.3,109.6
XS GIS Cut Line= 3
       1798454.2      203495.277     1798468.064      203746.386
      1798556.21       203974.11
#Sta/Elev= 30
       0 1432.98      29 1429.66    38.7 1428.02    48.4 1425.71      58 1422.94
    77.4 1416.79   94.251410.879   106.4 1405.88  114.88 1403.11   116.1 1402.71
   125.8 1402.36   135.4 1403.24  141.921403.784   154.8 1404.59   203.1 1406.34
   222.5 1407.32  296.721412.272   329.6 1413.91   339.4    1415  348.051416.642
   358.9 1419.06  377.631423.679   407.8 1431.33   417.5 1433.46   427.3 1435.21
   437.1  1436.5   466.4 1439.54  476.681441.313   485.9 1443.58   495.7 1446.57
#Mann= 9 ,-1 , 0
       0     .06       0   94.25     .12       0  114.88    .045       0
   135.4     .12       0  141.92     .06       0  296.72    .016       0
  348.05     .12       0  377.63     .06       0  476.68     .12       0
Bank Sta=114.88,135.4
XS Rating Curve= 0 ,0
Exp/Cntr=0.3,0.1

Type RM Length L Ch R = 1 ,4916.6  ,229.8,198.7,167.6
XS GIS Cut Line= 3
      1798339.84      203498.366     1798359.372      203718.418
     1798472.653      203948.887
#Sta/Elev= 30
       0 1432.46    19.2 1430.29   31.721428.566    38.4 1427.32      48 1424.86
    57.6 1421.93    86.4 1411.79   105.7 1405.71   115.3    1403   124.9 1401.31
   134.5 1400.92   144.1  1401.2   146.71401.314  154.921401.665   201.7 1403.22
   220.9  1403.6   268.5 1405.08     278 1405.64   287.5  1406.6  332.611412.076
  345.941413.573   363.6 1415.22   373.1 1415.59   382.6 1416.28   388.71417.423
   392.1 1418.06   430.2 1427.59   449.2 1432.12   458.7 1434.18   477.7 1437.33
#Mann= 9 ,-1 , 0
       0     .08       0   31.72     .06       0   124.9    .045       0
   144.1     .06       0   146.7     .12       0  154.92     .06       0
  332.61     .12       0  345.94    .016       0   388.7     .12       0
Bank Sta=124.9,144.1
XS Rating Curve= 0 ,0
Exp/Cntr=0.3,0.1

Type RM Length L Ch R = 1 ,4717.9  ,119.9,135.8,151.5
XS GIS Cut Line= 4
     1798075.517      203685.866     1798167.953      203778.416
     1798351.559      203800.449     1798454.424      203956.699
#Sta/Elev= 30
       0 1411.57     9.3 1409.81    18.7 1408.24      28 1407.08    37.4  1406.2
    93.4 1402.08   102.8 1401.57   130.8 1400.79  155.991399.745   198.9 1398.05
   218.4  1396.8   228.1 1396.46  233.831396.767   237.9 1396.99   257.3  1399.1
  282.631401.161     306 1402.96   325.1 1404.84   334.4 1406.16  387.681414.424
   390.6 1414.85   409.3 1416.12   418.6 1417.61  422.371418.573     428 1420.01
   437.3 1422.65   446.7 1425.15   465.4  1429.6   484.1 1433.58   502.8 1437.02
#Mann= 7 ,-1 , 0
       0     .06       0  155.99     .12       0   218.4    .045       0
  233.83     .12       0  282.63     .06       0  387.68    .016       0
  422.37     .12       0
Bank Sta=218.4,233.83
XS Rating Curve= 0 ,0
Exp/Cntr=0.3,0.1

Type RM Length L Ch R = 1 ,4582.1  ,244.5,240.1,235.9
XS GIS Cut Line= 2
     1798024.736      203722.324     1798332.028      204047.845
#Sta/Elev= 30
       0 1413.75     9.7 1411.67    29.2 1408.48    38.9 1407.04    48.7 1405.76
    58.4 1404.87    68.1 1404.52    87.6 1404.16  188.211400.741   214.1 1399.98
   223.8 1399.59   233.6  1398.8   243.7 1397.36     253 1396.55  260.461397.359
   272.5 1399.04     292 1400.83   301.7  1402.7   311.4 1406.09  321.961410.656
   330.9 1414.46  336.291416.405   340.6 1417.96   350.3 1419.73   360.1 1420.45
   369.8 1421.38  380.911423.273   408.7 1428.33   428.2  1432.2   447.6 1436.21
#Mann= 7 ,-1 , 0
       0     .06       0  188.21     .12       0   243.7    .045       0
  260.46     .12       0  321.96     .06       0  336.29    .016       0
  380.91     .12       0
Bank Sta=243.7,260.46
XS Rating Curve= 0 ,0
Exp/Cntr=0.3,0.1

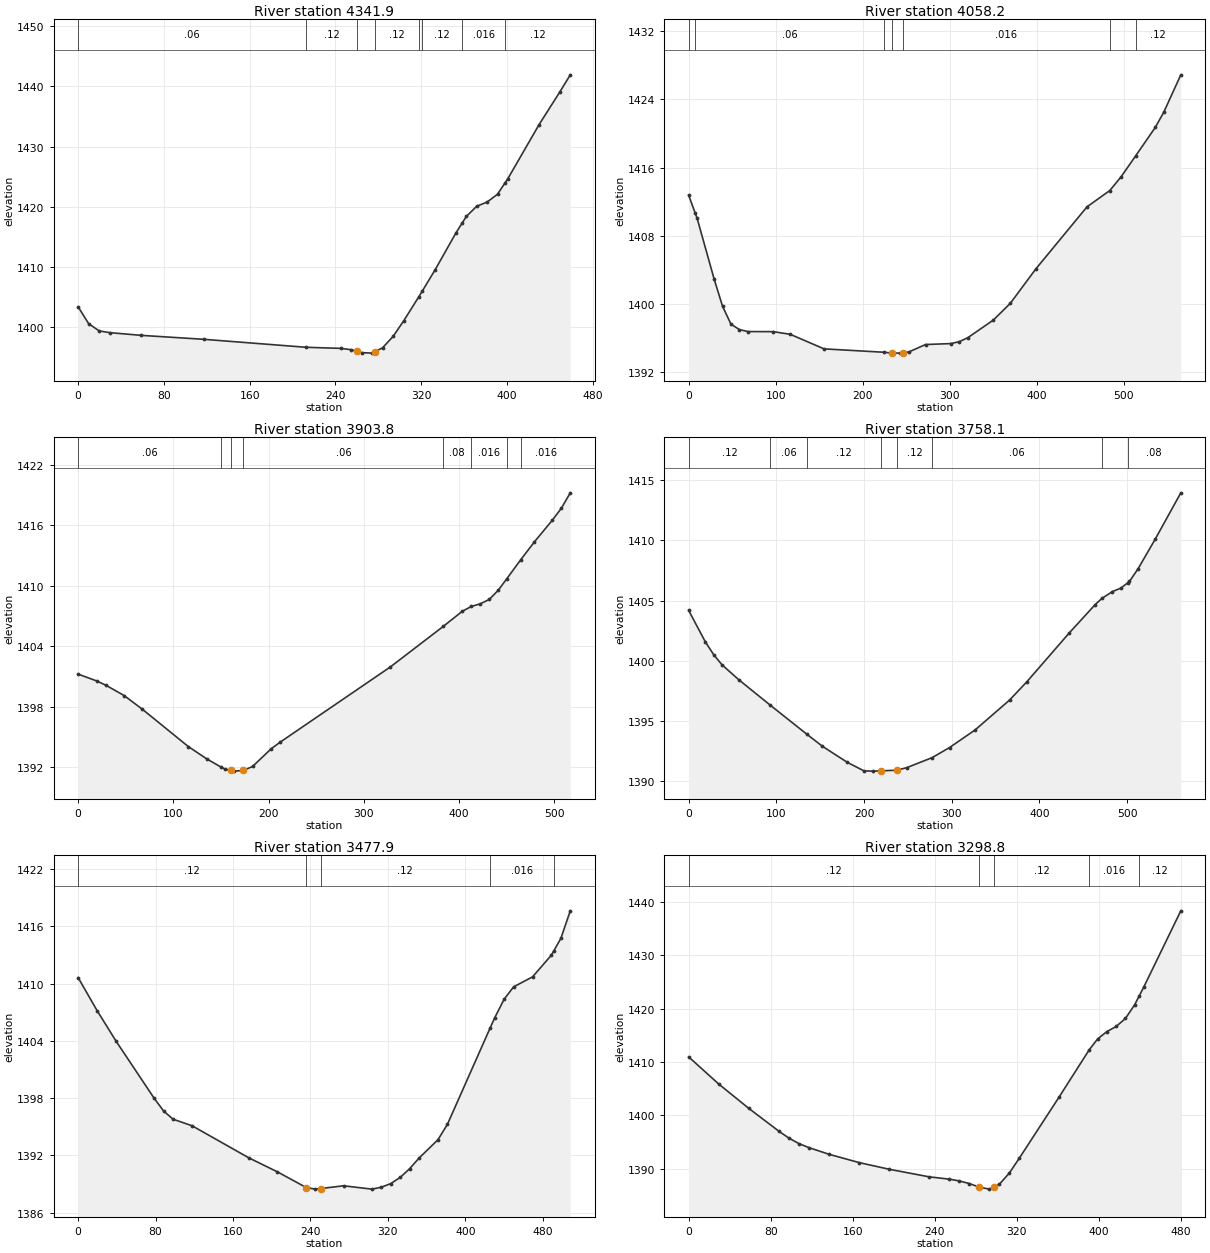
Type RM Length L Ch R = 1 ,4341.9  ,281.1,283.7,286.1
XS GIS Cut Line= 3
     1797850.257      203934.564     1798123.695      204124.668
     1798244.788      204159.824
#Sta/Elev= 30
       0 1403.39     9.8  1400.6    19.6  1399.4    29.4 1399.11    58.8 1398.66
   117.5    1398   212.71396.679   244.9  1396.5   254.7 1396.28  260.531395.989
   264.5 1395.79   274.3 1395.71   277.21395.975     284  1396.6   293.8 1398.48
   303.6 1401.04  317.571405.004  320.891405.963     333 1409.54   352.4 1415.65
   358.31417.317   362.1 1418.39   371.8 1420.09   381.5 1420.78   391.2 1422.08
  398.421424.015   400.9 1424.68     430 1433.64   449.4 1439.08   459.1  1441.9
#Mann= 8 ,-1 , 0
       0     .06       0   212.7     .12       0  260.53    .045       0
   277.2     .12       0  317.57     .06       0  320.89     .12       0
   358.3    .016       0  398.42     .12       0
Bank Sta=260.53,277.2
XS Rating Curve= 0 ,0
Exp/Cntr=0.3,0.1

Type RM Length L Ch R = 1 ,4058.2  ,161.9,154.4,145
XS GIS Cut Line= 3
     1797697.913      204135.085     1797968.747      204372.064
     1798174.476      204378.574
#Sta/Elev= 30
       0 1412.74    7.281410.721     9.7 1410.05    29.2 1402.94    38.9 1399.73
    48.6 1397.62    58.4 1396.98    68.1 1396.75    97.3 1396.74   116.7 1396.43
   155.6 1394.72  224.341394.323   233.4 1394.23   243.2 1394.22  246.411394.263
   252.9 1394.35   272.3 1395.23   301.5 1395.34   311.2 1395.57     321 1396.04
   350.2  1398.1   369.7 1400.06   399.1 1404.11   457.9 1411.39  484.121413.305
   497.1 1414.92  513.691417.354   536.3  1420.7   546.1 1422.49   565.7 1426.88
#Mann= 7 ,-1 , 0
       0     .12       0    7.28     .06       0  224.34    .016       0
   233.4    .045       0  246.41    .016       0  484.12     .06       0
  513.69     .12       0
Bank Sta=233.4,246.41
XS Rating Curve= 0 ,0
Exp/Cntr=0.3,0.1

Type RM Length L Ch R = 1 ,3903.8  ,151.2,145.7,130.4
XS GIS Cut Line= 3
     1797644.528      204359.043     1797950.517       204476.23
      1798139.32      204484.043
#Sta/Elev= 28
       0 1401.24    19.3 1400.57    28.9 1400.15    48.2 1399.12    67.5 1397.75
   115.6 1394.06   134.9 1392.84  150.081392.017   154.2 1391.82  160.131391.693
   163.8 1391.62   173.5 1391.69   183.1 1392.08   202.4 1393.82     212 1394.49
   327.7 1401.95   383.21405.969   403.2 1407.47  412.791407.953   422.1 1408.21
   431.6 1408.65     441 1409.56   449.81410.681  464.731412.605   478.8 1414.34
   497.7  1416.5   507.2 1417.69   516.6 1419.22
#Mann= 8 ,-1 , 0
       0     .06       0  150.08     .12       0  160.13    .045       0
   173.5     .06       0   383.2     .08       0  412.79    .016       0
   449.8     .06       0  464.73    .016       0
Bank Sta=160.13,173.5
XS Rating Curve= 0 ,0
Exp/Cntr=0.3,0.1

Type RM Length L Ch R = 1 ,3758.1  ,196.5,280.2,302.3
XS GIS Cut Line= 3
     1797603.617      204384.923     1797735.637      204535.112
     1798096.965      204537.282
#Sta/Elev= 29
       0 1404.19      19 1401.58    28.6 1400.51    38.1 1399.67    57.1 1398.44
    93.21396.316  134.86 1393.91   152.4 1392.92   180.9 1391.58     200 1390.87
  209.75 1390.85   219.5 1390.87   237.7 1390.93   248.8 1391.14  277.551391.966
   297.6 1392.81   326.9 1394.28     366 1396.75   385.5 1398.25   434.3 1402.34
   463.6 1404.67  471.311405.189   483.2 1405.75   492.9 1406.04  500.851406.486
   502.7 1406.59   512.5 1407.64     532 1410.09   561.3 1413.95
#Mann= 8 ,-1 , 0
       0     .12       0    93.2     .06       0  134.86     .12       0
   219.5    .045       0   237.7     .12       0  277.55     .06       0
  471.31    .016       0  500.85     .08       0
Bank Sta=219.5,237.7
XS Rating Curve= 0 ,0
Exp/Cntr=0.3,0.1

Type RM Length L Ch R = 1 ,3477.9  ,180.3,179.2,177.6
XS GIS Cut Line= 3
     1797508.206       204425.52     1797638.415      204585.025
     1797756.131        204863.8
#Sta/Elev= 30
       0 1410.63    19.6 1407.17    39.2 1403.97    78.4 1398.01    88.2 1396.67
      98  1395.8   117.7 1395.11   176.5 1391.74   205.9 1390.28   235.6 1388.64
     245 1388.47   250.6 1388.53   274.2 1388.82   303.5 1388.47   313.3 1388.67
     323 1389.05   332.8  1389.7   342.6 1390.62   352.3 1391.73   371.8 1393.65
   381.6 1395.27  425.561405.327   430.4 1406.42   440.2 1408.38   449.9 1409.66
   469.5 1410.71     489 1412.99  491.571413.452   498.8 1414.75   508.5 1417.63
#Mann= 5 ,-1 , 0
       0     .12       0   235.6    .045       0   250.6     .12       0
  425.56    .016       0  491.57     .06       0
Bank Sta=235.6,250.6
XS Rating Curve= 0 ,0
Exp/Cntr=0.3,0.1

Type RM Length L Ch R = 1 ,3298.8  ,326.4,335.2,341.5
XS GIS Cut Line= 4
     1797429.684      204503.574     1797509.111      204576.491
     1797622.392      204825.189     1797627.601      204924.147
#Sta/Elev= 30
       0 1410.97    29.4 1405.88    58.8 1401.31    88.2 1397.03      98 1395.73
   107.8 1394.71   117.6 1393.96   137.1 1392.72   166.4 1391.17   195.7 1389.92
   234.7  1388.5   254.2 1388.07     264 1387.74   273.7 1387.25   283.5 1386.58
   293.3  1386.2  297.471386.574     303 1387.07   312.8 1389.19   322.5 1391.96
   361.6  1403.5  390.961412.342   399.1 1414.35   408.1 1415.72   417.1 1416.67
   426.2 1418.18   435.2 1420.75  439.331422.292   444.2 1424.11   480.2 1438.34
#Mann= 5 ,-1 , 0
       0     .12       0   283.5    .045       0  297.47     .12       0
  390.96    .016       0  439.33     .12       0
Bank Sta=283.5,297.47
XS Rating Curve= 0 ,0
Exp/Cntr=0.3,0.1

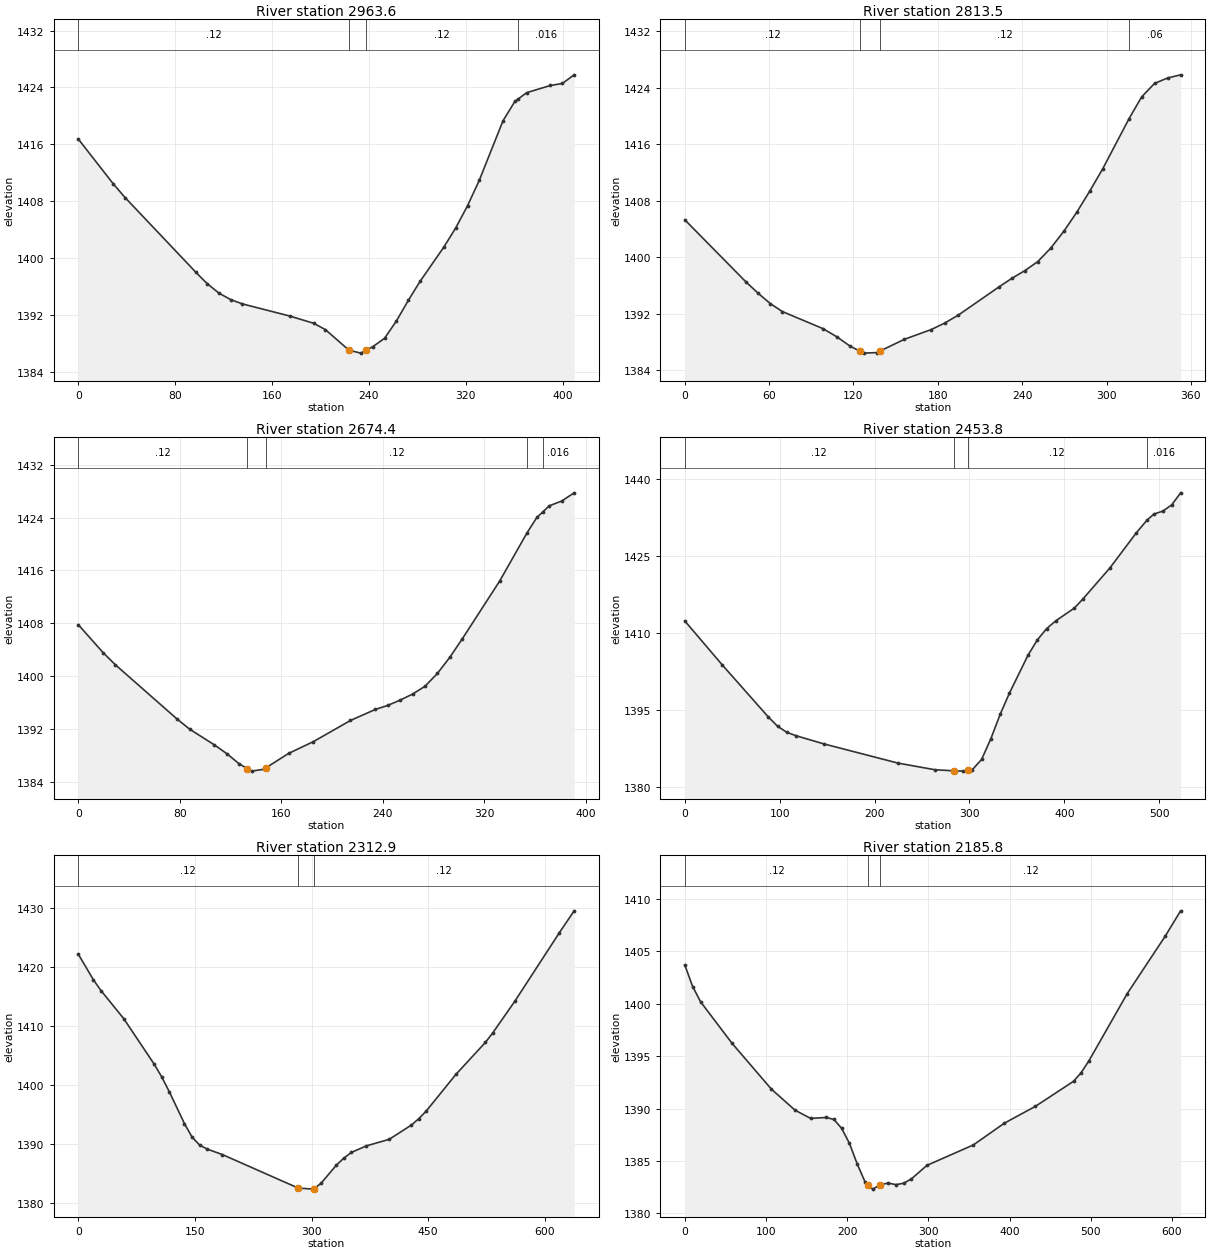
Type RM Length L Ch R = 1 ,2963.6  ,151.8,150.1,148.3
XS GIS Cut Line= 3
     1797260.413      204589.512     1797315.101      204702.793
     1797352.861      204984.043
#Sta/Elev= 30
       0 1416.73      29  1410.4    38.7 1408.48    96.8 1398.03   106.4 1396.38
   116.1 1395.05   125.8 1394.13   135.6 1393.52   174.7 1391.81   194.3  1390.8
   204.1  1389.9   223.6    1387   233.4 1386.59  237.72 1386.99   243.2 1387.49
     253 1388.68   262.8 1391.13   272.6 1394.02   282.4 1396.72   301.9 1401.51
   311.7  1404.2   321.5 1407.34   331.3 1410.96   350.8  1419.3   360.6 1422.03
  363.231422.363   370.4 1423.27     390 1424.28   399.8 1424.56   409.6 1425.78
#Mann= 4 ,-1 , 0
       0     .12       0   223.6    .045       0  237.72     .12       0
  363.23    .016       0
Bank Sta=223.6,237.72
XS Rating Curve= 0 ,0
Exp/Cntr=0.3,0.1

Type RM Length L Ch R = 1 ,2813.5  ,149.3,139.1,128.8
XS GIS Cut Line= 4
     1797140.622      204680.657     1797175.778      204740.553
     1797205.726      204891.595     1797290.361      204989.251
#Sta/Elev= 30
       0 1405.29    43.4 1396.51    52.1  1394.9    60.8 1393.42    69.4 1392.29
    98.3 1389.87     108 1388.73   117.6 1387.39  124.771386.653   127.2  1386.4
   136.8 1386.48  139.061386.714   156.1 1388.35   175.3 1389.74   184.9 1390.66
   194.6 1391.79   223.4 1395.77   232.7    1397   241.9 1398.09   251.1 1399.37
   260.4  1401.3   269.6 1403.66   278.8 1406.35     288 1409.34   297.3 1412.52
  315.941419.593     325 1422.71   334.2 1424.62   343.4 1425.38   352.7 1425.83
#Mann= 4 ,-1 , 0
       0     .12       0  124.77    .045       0  139.06     .12       0
  315.94     .06       0
Bank Sta=124.77,139.06
XS Rating Curve= 0 ,0
Exp/Cntr=0.3,0.1

Type RM Length L Ch R = 1 ,2674.4  ,209.7,220.5,229.8
XS GIS Cut Line= 3
     1796986.976      204758.782     1797132.809      204954.095
      1797246.09      205047.845
#Sta/Elev= 30
       0 1407.81    19.5  1403.6    29.2 1401.76      78 1393.54    87.8 1392.03
   107.2 1389.67     117 1388.34   126.8  1386.8   133.1 1386.09   136.5  1385.7
   146.2 1385.98   148.1 1386.23   165.8 1388.38   185.2 1390.15   214.5 1393.35
     234 1395.01   243.8 1395.62   253.6 1396.42   263.4 1397.33   273.2 1398.51
     283 1400.45   292.8 1402.89   302.6 1405.67     332 1414.38  353.621421.676
   361.4 1424.01  365.851424.809   371.2 1425.77     381 1426.49   390.8 1427.73
#Mann= 5 ,-1 , 0
       0     .12       0   133.1    .045       0   148.1     .12       0
  353.62     .06       0  365.85    .016       0
Bank Sta=133.1,148.1
XS Rating Curve= 0 ,0
Exp/Cntr=0.3,0.1

Type RM Length L Ch R = 1 ,2453.8  ,136,140.9,147.2
XS GIS Cut Line= 3
     1796901.038      204778.314     1797005.205      205175.449
     1797098.955      205236.647
#Sta/Elev= 30
       0  1412.3    39.1  1403.8      88 1393.57    97.8 1391.75   107.5 1390.57
   117.3  1389.9   146.6 1388.31   224.8 1384.56   263.9 1383.26   283.5 1383.06
   293.3    1383  298.211383.143     303 1383.28   312.8 1385.29   322.6 1389.36
   332.4 1394.11   342.1 1398.22   361.7 1405.62   371.5 1408.59   381.2 1410.78
     391 1412.33   410.6 1414.82   419.9 1416.66   447.9 1422.62   475.9 1429.51
  486.961431.944   494.5 1433.16   503.9 1433.73   513.2 1434.96   522.5 1437.29
#Mann= 4 ,-1 , 0
       0     .12       0   283.5    .045       0  298.21     .12       0
  486.96    .016       0
Bank Sta=283.5,298.21
XS Rating Curve= 0 ,0
Exp/Cntr=0.3,0.1

Type RM Length L Ch R = 1 ,2312.9  ,137.4,127.1,115.1
XS GIS Cut Line= 3
     1796846.351      204741.855     1796837.236      205141.595
     1797044.267      205258.782
#Sta/Elev= 30
       0  1422.1    19.5 1417.75    29.3 1415.92    58.5 1411.18    97.5  1403.5
   107.3 1401.32     117 1398.82   136.5 1393.42   146.3 1391.14     156 1389.79
   165.8 1389.11   185.3 1388.18   282.8 1382.51   302.3 1382.33  303.361382.436
   312.1 1383.31   331.6 1386.35   341.3 1387.56   351.1 1388.54   370.6 1389.66
   399.8 1390.76   428.4 1393.18   437.9 1394.26   447.4 1395.54   485.5 1401.74
   523.6 1407.18   533.1  1408.8   561.6 1414.18   618.7 1425.75   637.7 1429.45
#Mann= 3 ,-1 , 0
       0     .12       0   282.8    .045       0  303.36     .12       0
Bank Sta=282.8,303.36
XS Rating Curve= 0 ,0
Exp/Cntr=0.3,0.1

Type RM Length L Ch R = 1 ,2185.8  ,117.7,108.3,99.1
XS GIS Cut Line= 4
     1796526.038      204965.814     1796679.684       204944.98
     1796798.174       205194.98     1796930.986      205314.772
#Sta/Elev= 30
       0 1403.71     9.7 1401.65    19.4  1400.2    58.1 1396.24   106.6 1391.86
   135.7 1389.85     155 1389.06   174.1 1389.15   183.7 1388.96   193.2 1388.11
   202.8 1386.67   212.3 1384.72   221.8 1383.03  225.761382.733   231.4 1382.31
   240.9 1382.73   250.4 1382.89     260 1382.74   269.5 1382.87   279.1 1383.29
   298.2 1384.58   355.4 1386.53   393.6 1388.61   431.7 1390.21   478.8 1392.61
   488.2 1393.44   497.6 1394.55   544.7 1400.96   591.7 1406.47   610.6 1408.88
#Mann= 3 ,-1 , 0
       0     .12       0  225.76    .045       0   240.9     .12       0
Bank Sta=225.76,240.9
XS Rating Curve= 0 ,0
Exp/Cntr=0.3,0.1

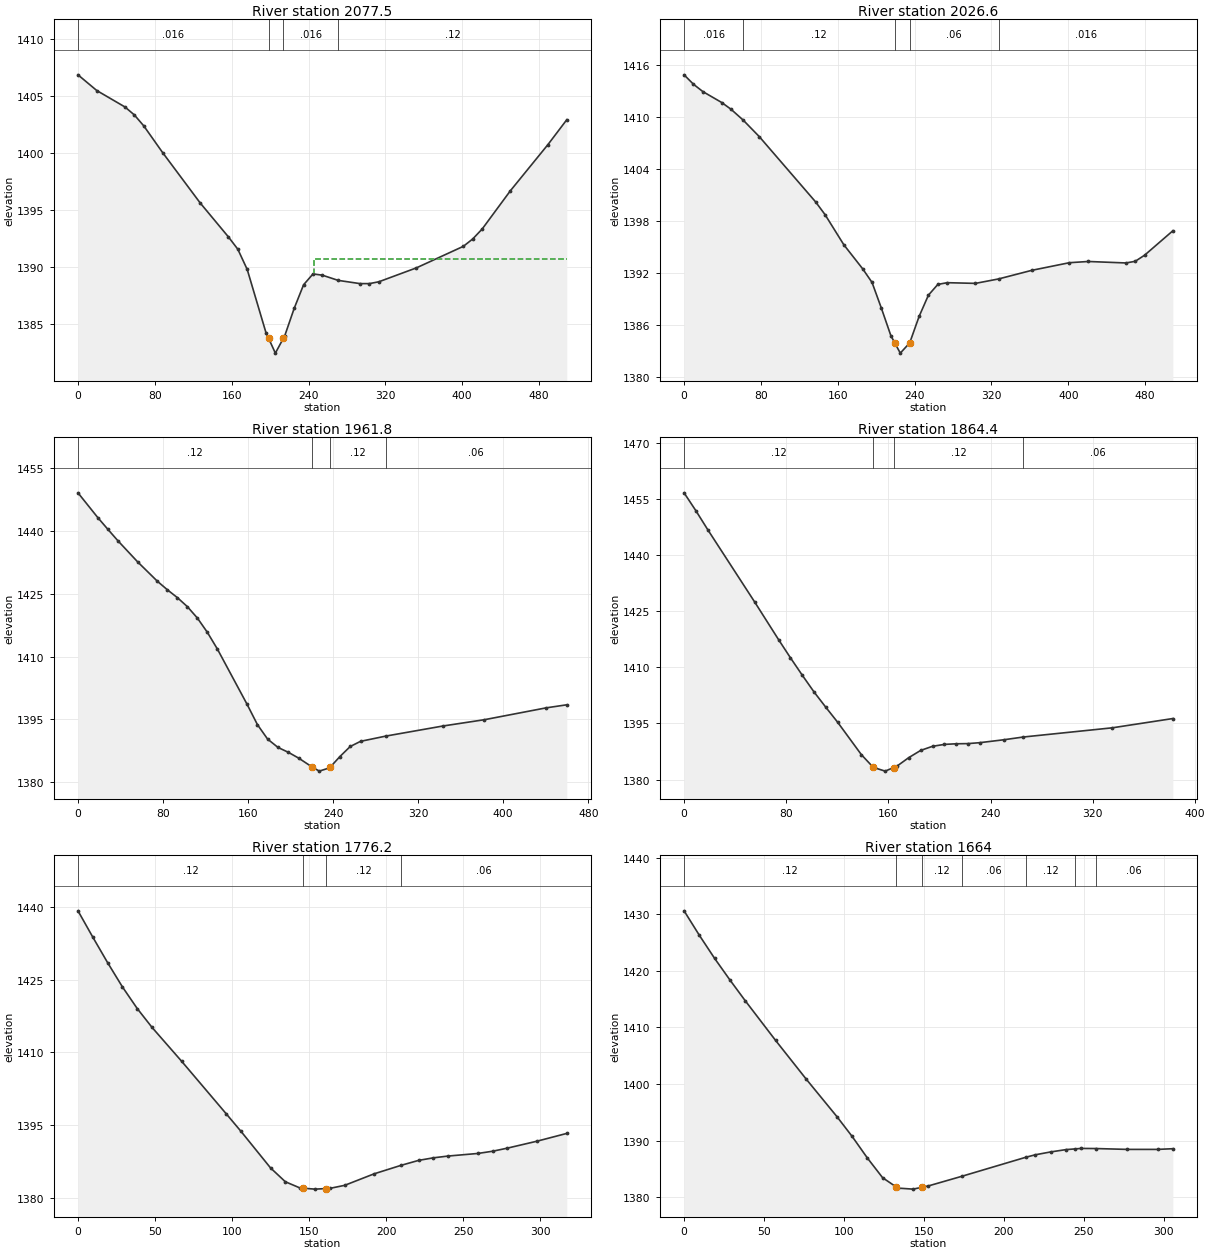
Type RM Length L Ch R = 1 ,2077.5  ,50.9,50.9,50.7
XS GIS Cut Line= 2
     1796519.528      204980.137     1796897.132      205321.282
#Sta/Elev= 30
       0  1406.9    19.6 1405.52    48.9 1404.08    58.7 1403.38    68.5 1402.42
    88.1 1400.08   127.2 1395.66   156.6 1392.68   166.4  1391.6   176.2 1389.82
   195.7 1384.28  198.431383.781   205.5 1382.48  213.88 1383.79   215.3 1384.01
   225.1 1386.41   234.9 1388.48   244.7 1389.43   254.4 1389.32   270.91388.863
   293.6 1388.58   303.4 1388.58   313.2 1388.74   352.3 1389.96   401.2 1391.85
     411  1392.5   420.8 1393.37   450.2 1396.73   489.3 1400.78   508.9 1402.96
#Mann= 4 ,-1 , 0
       0    .016       0  198.43    .045       0  213.88    .016       0
   270.9     .12       0
#XS Ineff= 2 , 0
                          245.82         1390.74
Permanent Ineff=
       F       F
Bank Sta=198.43,213.88
XS Rating Curve= 0 ,0
Exp/Cntr=0.3,0.1

Type RM Length L Ch R = 1 ,2026.6  ,66.2,64.8,63.5
XS GIS Cut Line= 2
     1796486.976      205013.991      1796864.58      205355.137
#Sta/Elev= 30
       0 1414.92     9.8 1413.83    19.6 1412.98    39.2 1411.72    48.9 1410.94
   61.581409.684    78.3 1407.78     137 1400.23   146.8 1398.76   166.4 1395.27
   185.9 1392.51   195.7 1390.93   205.5 1387.93   215.3 1384.78   219.41383.935
   225.1 1382.76   234.9 1383.94   244.7    1387   254.4 1389.46   264.2  1390.7
     274  1390.9   303.4 1390.82  327.421391.333   362.1 1392.33   401.2 1393.21
   420.8 1393.35     460 1393.18   469.7 1393.37   479.5 1394.08   508.9  1396.9
#Mann= 5 ,-1 , 0
       0    .016       0   61.58     .12       0   219.4    .045       0
   234.9     .06       0  327.42    .016       0
Bank Sta=219.4,234.9
XS Rating Curve= 0 ,0
Exp/Cntr=0.3,0.1

Type RM Length L Ch R = 1 ,1961.8  ,112.2,97.4,81.7
XS GIS Cut Line= 3
     1796412.757      205170.241     1796571.611      205178.053
     1796804.684      205368.157
#Sta/Elev= 30
       0 1449.01    18.7 1443.09    28.1 1440.32    37.4 1437.63    56.1 1432.56
    74.8 1427.91    84.2 1425.88    93.6 1424.01   102.9 1421.88   112.3 1419.17
   121.6  1415.8     131 1411.84     159 1398.64   168.8 1393.76   178.4 1390.31
   188.2 1388.32   197.9 1387.16   207.6 1385.78  220.131383.681     227 1382.68
   236.7 1383.47  237.531383.699   246.4 1386.16   256.1 1388.55   265.8 1389.78
  289.56 1391.03   343.4 1393.44   382.2 1394.93   440.4 1397.76   459.8 1398.49
#Mann= 4 ,-1 , 0
       0     .12       0  220.13    .045       0  237.53     .12       0
  289.56     .06       0
Bank Sta=220.13,237.53
XS Rating Curve= 0 ,0
Exp/Cntr=0.3,0.1

Type RM Length L Ch R = 1 ,1864.4  ,87,88.1,89.2
XS GIS Cut Line= 4
     1796417.965      205256.178     1796532.549      205292.637
     1796680.986      205296.543     1796773.434      205362.949
#Sta/Elev= 26
       0 1456.57     9.2 1451.82    18.5 1446.75    55.5  1427.3      74 1417.36
    83.2 1412.56    92.5 1407.89   101.7 1403.42     111  1399.3   120.2 1395.33
   138.8 1386.66   148.1 1383.27   157.4 1382.27  163.94 1383.21   166.6 1383.59
   175.9 1385.88   185.2  1387.8   194.5  1388.9   203.8 1389.41     213 1389.57
   222.3 1389.62   231.6 1389.87   250.2 1390.64  265.581391.379   335.1 1393.83
   382.6 1396.31
#Mann= 4 ,-1 , 0
       0     .12       0   148.1    .045       0  163.94     .12       0
  265.58     .06       0
Bank Sta=148.1,163.94
XS Rating Curve= 0 ,0
Exp/Cntr=0.3,0.1

Type RM Length L Ch R = 1 ,1776.2  ,108.7,112.3,115.5
XS GIS Cut Line= 2
     1796432.288      205366.855     1796748.695      205390.293
#Sta/Elev= 27
       0 1439.17     9.6 1433.76    19.2 1428.51    28.8 1423.52    38.5 1419.02
    48.1 1415.14    67.3 1408.17    96.1  1397.4   105.8 1393.74     125  1386.2
   134.6 1383.35   144.2 1382.06     146 1382.02   153.8 1381.83     161 1381.94
   163.4 1381.98   173.1 1382.61   192.3 1384.99  209.641386.724   221.1 1387.75
   230.7 1388.28   240.4 1388.65   259.6 1389.18   269.2 1389.64   278.8 1390.28
     298 1391.71   317.3 1393.31
#Mann= 4 ,-1 , 0
       0     .12       0     146    .045       0     161     .12       0
  209.64     .06       0
Bank Sta=146,161
XS Rating Curve= 0 ,0
Exp/Cntr=0.3,0.1

Type RM Length L Ch R = 1 ,1664    ,119.3,123.5,127.6
XS GIS Cut Line= 2
     1796425.778      205456.699     1796723.955      205524.407
#Sta/Elev= 27
       0 1430.58     9.6 1426.24    19.1 1422.18    28.7 1418.36    38.2 1414.72
    57.3 1407.67    76.4 1400.85    95.6 1394.23   105.1 1390.74   114.7  1386.9
   124.2 1383.43  132.721381.795   133.8 1381.59   143.3 1381.41  149.151381.755
   152.9 1381.98  173.751383.677  214.131387.067   219.8 1387.48   229.3 1387.98
   238.9 1388.39  244.541388.515   248.4  1388.6  257.481388.581   277.1 1388.43
   296.2 1388.43   305.8 1388.55
#Mann= 7 ,-1 , 0
       0     .12       0  132.72    .045       0  149.15     .12       0
  173.75     .06       0  214.13     .12       0  244.54     .04       0
  257.48     .06       0
Bank Sta=132.72,149.15
XS Rating Curve= 0 ,0
Exp/Cntr=0.3,0.1