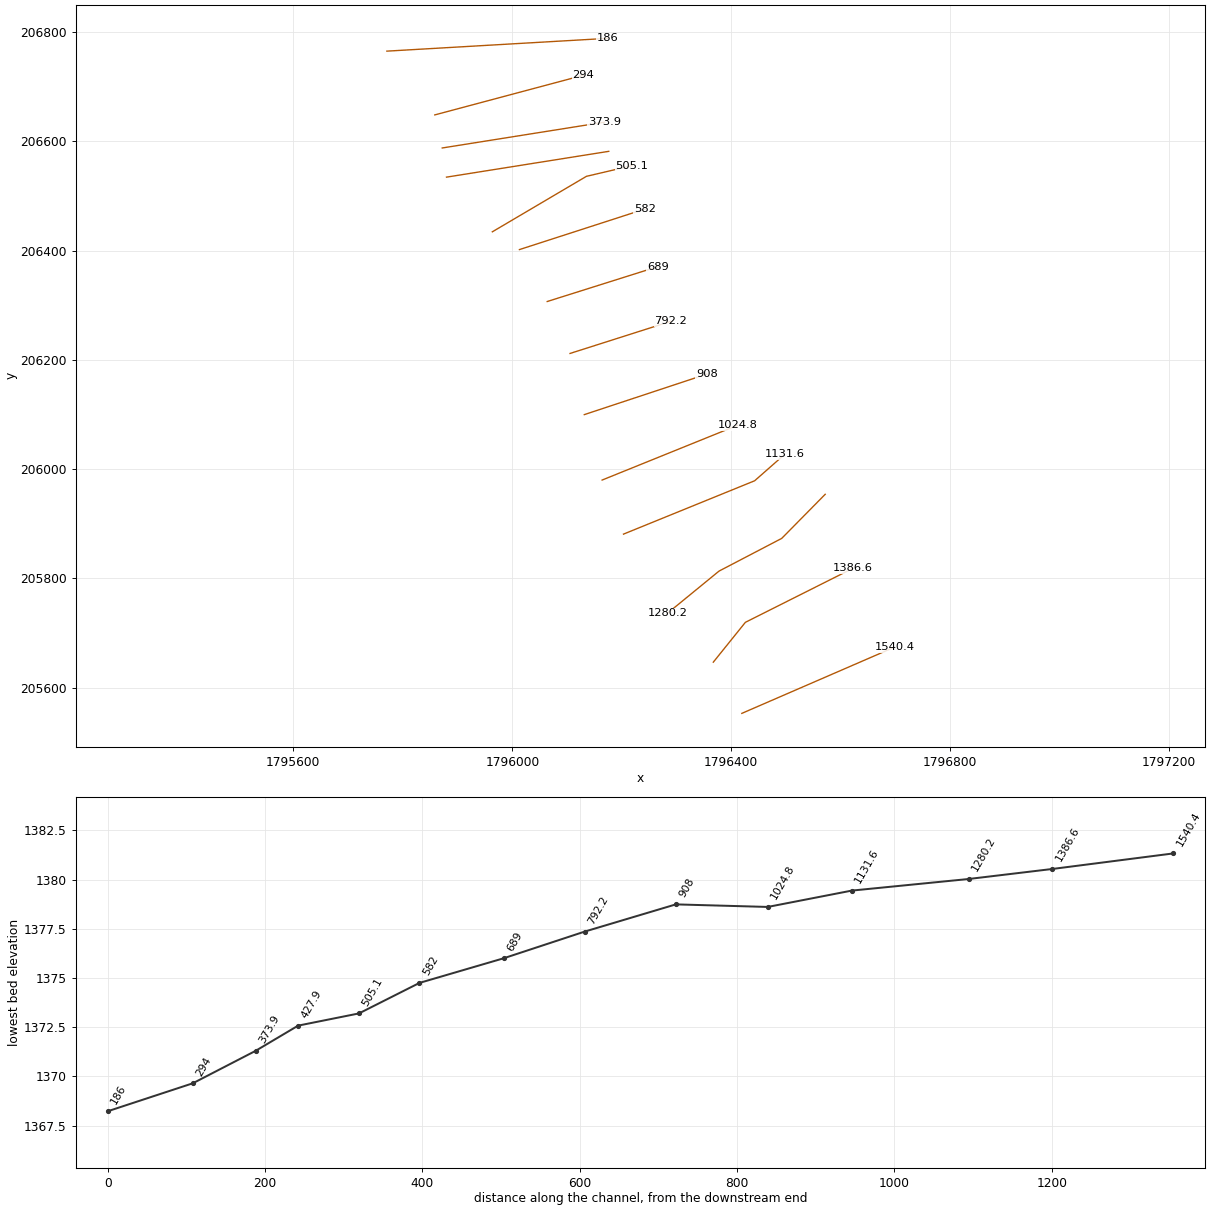
HEC-RAS study LKSHOALSRN.prj: LKSHOALSRN

--- LKSHOALSRN.g01 (geometry) --- (continued)

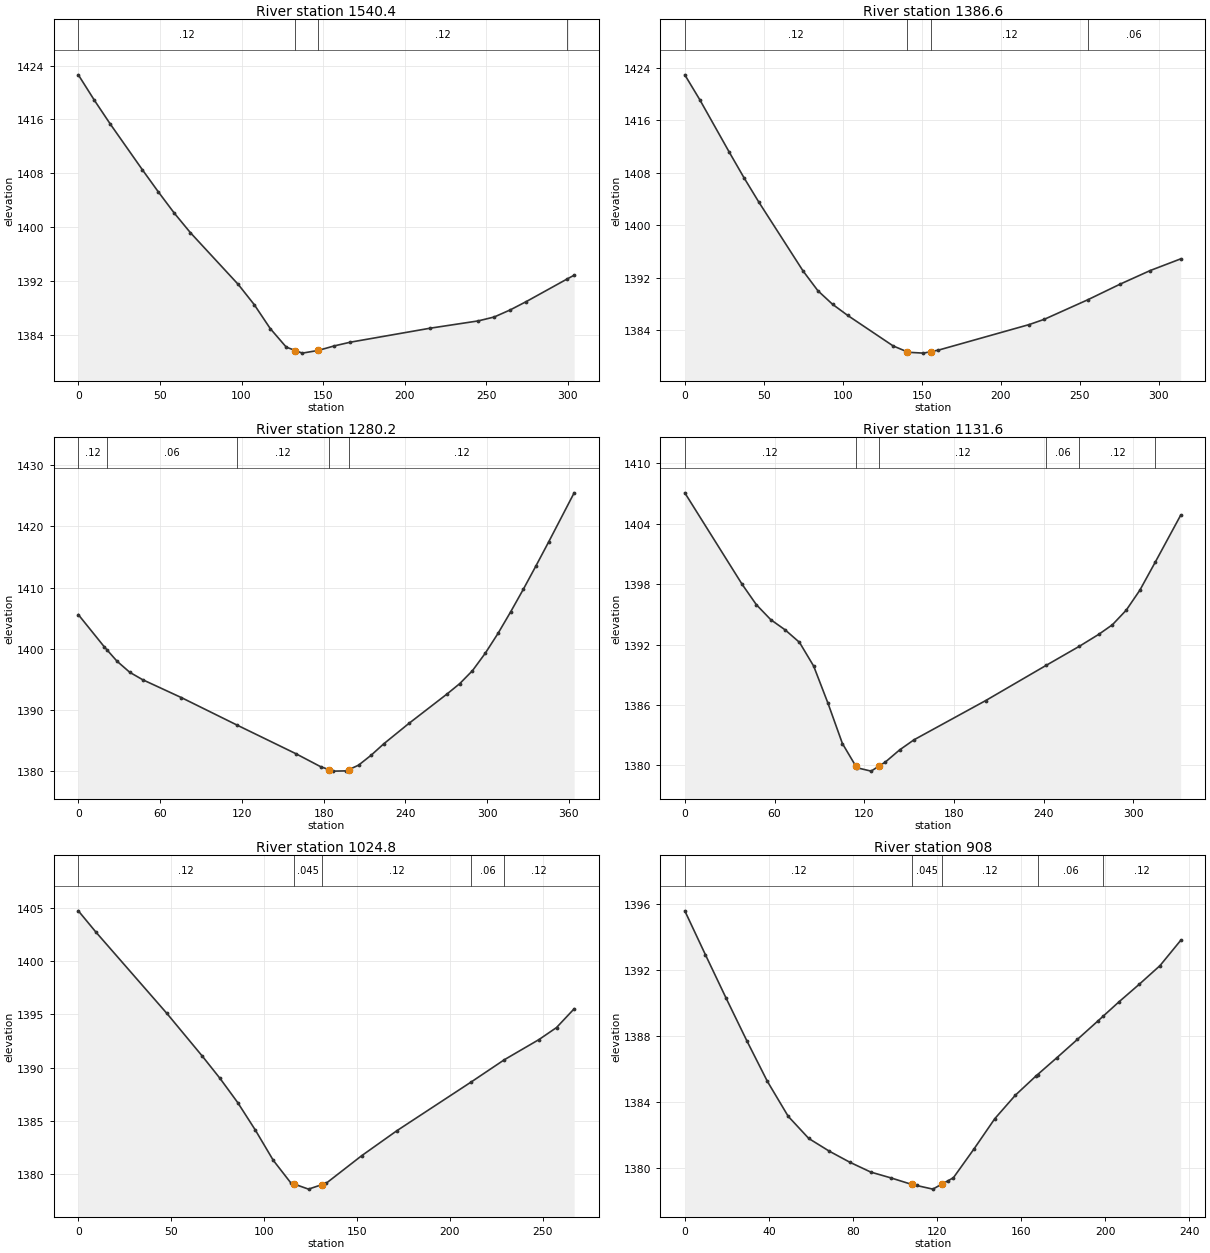
Type RM Length L Ch R = 1 ,1540.4  ,152.6,153.8,155.1
XS GIS Cut Line= 2
     1796419.267      205553.053     1796697.913      205674.147
#Sta/Elev= 23
       0 1422.62     9.8 1418.86    19.6 1415.31    39.2 1408.55      49 1405.26
    58.8  1402.1    68.6 1399.22      98 1391.52   107.8 1388.52   117.6 1384.97
   127.4 1382.22  132.971381.716   137.2 1381.33     147 1381.73   156.8  1382.4
   166.6 1382.95   215.6 1385.03     245 1386.11   254.8 1386.69   264.6 1387.74
   274.4 1388.97  299.651392.352   303.8 1392.89
#Mann= 4 ,-1 , 0
       0     .12       0  132.97    .045       0     147     .12       0
  299.65     .06       0
Bank Sta=132.97,147
XS Rating Curve= 0 ,0
Exp/Cntr=0.3,0.1

Type RM Length L Ch R = 1 ,1386.6  ,106,106.5,106.7
XS GIS Cut Line= 3
     1796367.184      205646.803     1796425.778       205719.72
     1796622.392      205818.678
#Sta/Elev= 21
       0 1422.95     9.4 1419.19    28.1 1411.18    37.4 1407.29    46.8 1403.57
    74.8 1393.07    84.2 1390.05    93.5 1387.98   103.1 1386.28   131.8 1381.64
   140.7 1380.74   141.4 1380.67     151 1380.54   155.7 1380.77   160.5    1381
     218  1384.9   227.5  1385.7  255.071388.683   275.4 1391.05   294.5 1393.13
   313.7  1394.9
#Mann= 4 ,-1 , 0
       0     .12       0   140.7    .045       0   155.7     .12       0
  255.07     .06       0
Bank Sta=140.7,155.7
XS Rating Curve= 0 ,0
Exp/Cntr=0.3,0.1

Type RM Length L Ch R = 1 ,1280.2  ,150.6,148.6,146.3
XS GIS Cut Line= 4
     1796571.611      205954.095     1796492.184      205873.366
     1796377.601       205813.47     1796283.851      205736.647
#Sta/Elev= 28
       0 1405.5918.89999 1400.37   21.221399.78628.39999 1397.9837.79999 1396.16
47.19998 1394.9675.59998 1392.04  116.64 1387.53   159.5 1382.89     178 1380.73
  183.961380.279   187.2 1380.03   196.4 1380.07  198.561380.286   205.6    1381
   214.9 1382.64   224.1 1384.49   242.6 1387.83   270.6 1392.64   279.9 1394.33
   289.2 1396.44   298.5 1399.26   307.9 1402.51   317.2 1406.04   326.5 1409.73
   335.8 1413.56   345.2 1417.51   363.8 1425.48
#Mann= 5 ,-1 , 0
       0     .12       0   21.22     .06       0  116.64     .12       0
  183.96    .045       0  198.56     .12       0
Bank Sta=183.96,198.56
XS Rating Curve= 0 ,0
Exp/Cntr=0.3,0.1

Type RM Length L Ch R = 1 ,1131.6  ,106.6,106.8,106.5
XS GIS Cut Line= 3
     1796203.122      205881.178     1796442.705      205978.835
     1796497.392      206027.012
#Sta/Elev= 25
       0 1407.06    38.3 1397.99    47.9 1395.95    57.5 1394.47    67.1 1393.46
    76.7 1392.22    86.2 1389.86    95.8 1386.16   105.4 1382.18  114.461379.913
     115 1379.78   124.6 1379.44  129.671379.922   134.2 1380.35   143.7 1381.55
   153.3 1382.55   201.2 1386.44  241.781389.946  263.951391.837   276.9 1393.02
     286 1393.97   295.2 1395.41   304.3 1397.39  314.711400.201   331.6 1404.83
#Mann= 6 ,-1 , 0
       0     .12       0  114.46    .045       0  129.67     .12       0
  241.78     .06       0  263.95     .12       0  314.71     .06       0
Bank Sta=114.46,129.67
XS Rating Curve= 0 ,0
Exp/Cntr=0.3,0.1

Type RM Length L Ch R = 1 ,1024.8  ,117.7,116.8,114.8
XS GIS Cut Line= 2
     1796164.059      205980.137     1796411.455      206080.397
#Sta/Elev= 20
       0 1404.69     9.5 1402.69    47.7 1395.07    66.7 1391.08    76.3 1388.98
    85.8 1386.72    95.3 1384.14   104.9 1381.32   114.4 1379.19   116.1 1379.09
   123.9 1378.61   131.1 1379.03   133.5 1379.17   152.5 1381.74   171.6  1384.1
   211.51388.654  229.391390.743   247.9 1392.62   257.4 1393.75   266.9 1395.51
#Mann= 5 ,-1 , 0
       0     .12       0   116.1    .045       0   131.1     .12       0
   211.5     .06       0  229.39     .12       0
Bank Sta=116.1,131.1
XS Rating Curve= 0 ,0
Exp/Cntr=0.3,0.1

Type RM Length L Ch R = 1 ,908     ,115.5,115.7,115
XS GIS Cut Line= 2
     1796131.507      206099.928     1796355.465      206174.147
#Sta/Elev= 30
       0 1395.56     9.8 1392.91    19.7 1390.27    29.5 1387.71    39.3 1385.25
    49.2 1383.14      59  1381.8    68.8 1381.03    78.6 1380.36    88.5 1379.77
    98.3 1379.41   108.1 1379.02   110.3 1378.96     118 1378.74  122.261379.038
   125.3 1379.25   127.8 1379.43   137.6 1381.17   147.5    1383   157.3 1384.42
   167.1 1385.58  167.871385.666     177 1386.68   186.8 1387.79   196.6 1388.91
  199.171389.206   206.4 1390.04   216.3 1391.13   226.1 1392.25   235.9 1393.77
#Mann= 5 ,-1 , 0
       0     .12       0   108.1    .045       0  122.26     .12       0
  167.87     .06       0  199.17     .12       0
Bank Sta=108.1,122.26
XS Rating Curve= 0 ,0
Exp/Cntr=0.3,0.1

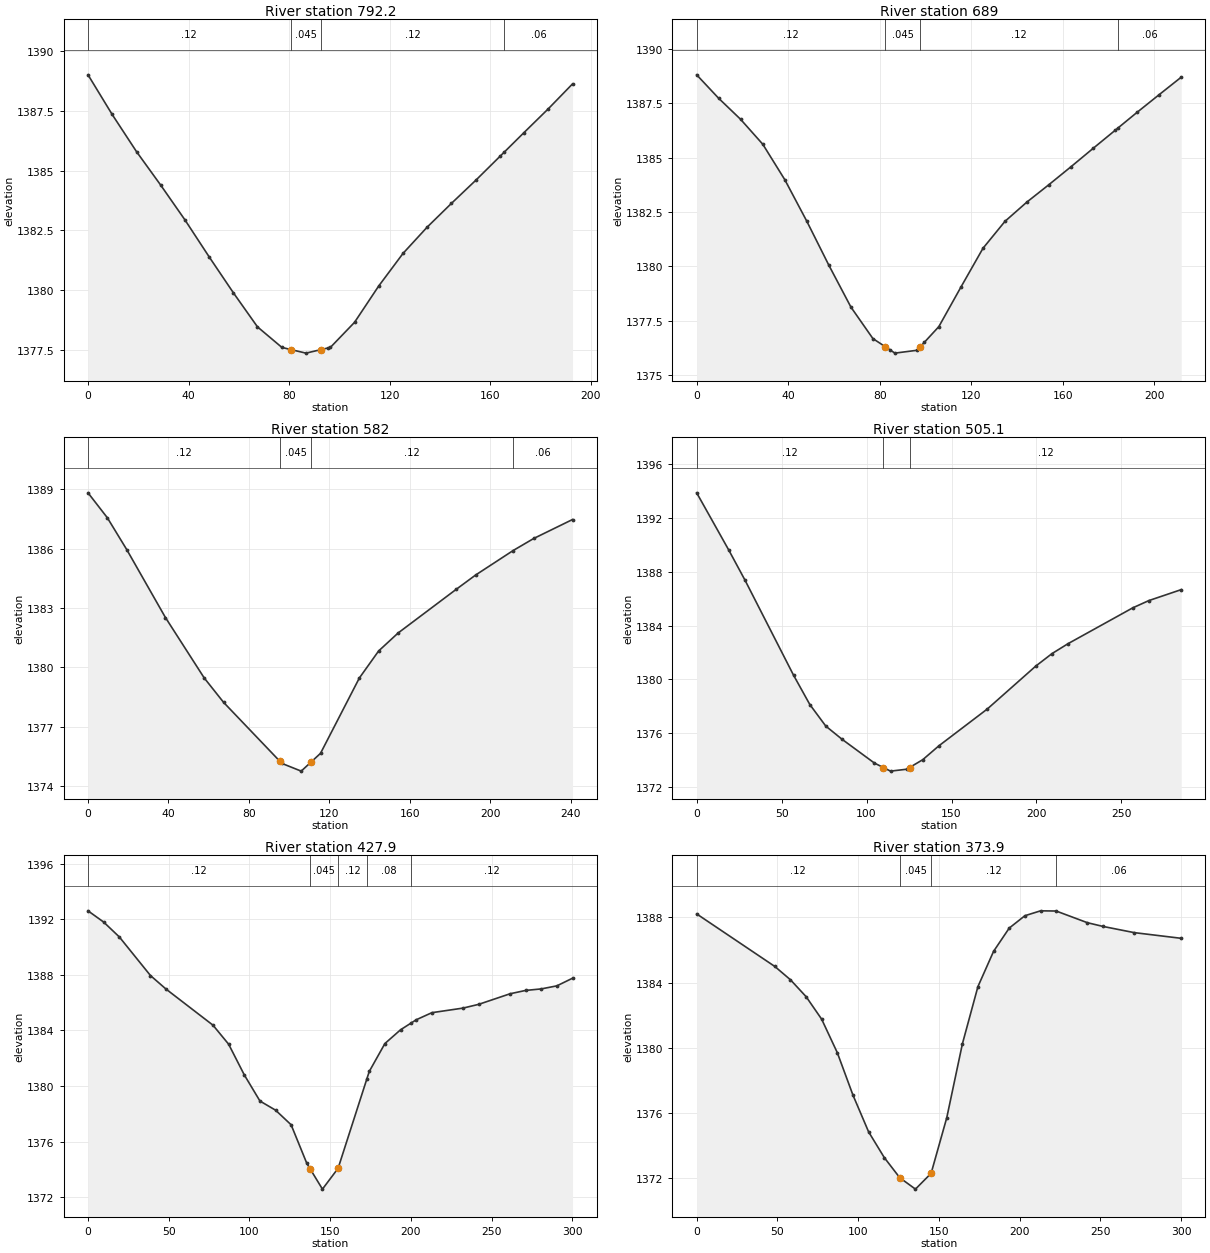
Type RM Length L Ch R = 1 ,792.2   ,103.6,103.3,103.5
XS GIS Cut Line= 2
     1796105.465      206211.907     1796289.059      206270.501
#Sta/Elev= 25
       0 1389.02     9.6 1387.36    19.3  1385.8    28.9  1384.4    38.5 1382.95
    48.2 1381.39    57.8 1379.89    67.4 1378.46    77.1  1377.6    80.6 1377.51
    86.7 1377.36   92.671377.508    95.6 1377.58    96.4  1377.6     106 1378.65
   115.6 1380.17   125.3 1381.54   134.9 1382.64   144.5 1383.63   154.2  1384.6
   163.8  1385.6   165.51385.777   173.4  1386.6   183.1  1387.6   192.7 1388.64
#Mann= 4 ,-1 , 0
       0     .12       0    80.6    .045       0   92.67     .12       0
   165.5     .06       0
Bank Sta=80.6,92.67
XS Rating Curve= 0 ,0
Exp/Cntr=0.3,0.1

Type RM Length L Ch R = 1 ,689     ,106.7,106.9,107
XS GIS Cut Line= 2
     1796063.799       206306.96     1796265.622      206370.762
#Sta/Elev= 28
       0 1388.82     9.6 1387.74    19.2 1386.77    28.9 1385.62    38.5 1383.99
    48.1 1382.08    57.7 1380.06    67.4 1378.12      77 1376.67   82.441376.293
    84.5 1376.15    86.6    1376    96.2 1376.13   97.671376.295    99.5  1376.5
   105.8 1377.22   115.5 1379.05   125.1 1380.83   134.7 1382.07   144.3 1382.96
   153.9 1383.76   163.6 1384.59   173.2 1385.43   182.8 1386.26  183.921386.357
   192.4 1387.09     202  1387.9   211.7 1388.71
#Mann= 4 ,-1 , 0
       0     .12       0   82.44    .045       0   97.67     .12       0
  183.92     .06       0
Bank Sta=82.44,97.67
XS Rating Curve= 0 ,0
Exp/Cntr=0.3,0.1

Type RM Length L Ch R = 1 ,582     ,71.8,76.9,81.7
XS GIS Cut Line= 2
     1796013.017      206402.012     1796242.184       206476.23
#Sta/Elev= 19
       0 1388.83     9.6 1387.57    19.3 1385.95    38.5 1382.52    57.8 1379.46
    67.4 1378.23   95.481375.239    96.4 1375.14     106 1374.75  111.081375.226
   115.6 1375.65   134.9 1379.46   144.5 1380.83   154.2 1381.74   183.1 1383.95
   192.7 1384.67   211.41385.912   221.6 1386.52   240.9 1387.48
#Mann= 4 ,-1 , 0
       0     .12       0   95.48    .045       0  111.08     .12       0
   211.4     .06       0
Bank Sta=95.48,111.08
XS Rating Curve= 0 ,0
Exp/Cntr=0.3,0.1

Type RM Length L Ch R = 1 ,505.1   ,85.8,77.3,68.8
XS GIS Cut Line= 3
     1795963.538      206434.564     1796135.413      206536.126
     1796218.747      206555.657
#Sta/Elev= 21
       0 1393.84      19 1389.57    28.5 1387.35      57 1380.32    66.6 1378.14
      76 1376.54    85.6 1375.56   104.6  1373.8  109.921373.464   114.1  1373.2
   123.6 1373.34  125.321373.469   133.1 1374.05   142.6 1375.08   171.1 1377.81
   199.6 1380.99   209.2 1381.92   218.7 1382.66   256.7 1385.31   266.2 1385.85
   285.2 1386.66
#Mann= 3 ,-1 , 0
       0     .12       0  109.92    .045       0  125.32     .12       0
Bank Sta=109.92,125.32
XS Rating Curve= 0 ,0
Exp/Cntr=0.3,0.1

Type RM Length L Ch R = 1 ,427.9   ,54.1,54,54.1
XS GIS Cut Line= 2
     1795879.815      206534.649     1796176.168      206581.874
#Sta/Elev= 29
       0 1392.61     9.7  1391.8    19.4 1390.73    38.7 1387.95    48.4 1386.97
    77.4 1384.38    87.1 1383.01    96.8  1380.8   106.5 1378.92   116.2 1378.26
   125.8 1377.21   135.5 1374.44  137.46 1374.06   145.2 1372.58   154.9 1374.08
  172.76 1380.53   174.2 1381.05   183.9 1383.06   193.6 1384.05  200.181384.538
   203.3 1384.77     213 1385.28   232.3 1385.61     242 1385.88   261.4 1386.64
     271 1386.88   280.7 1386.99   290.4 1387.21   300.1 1387.76
#Mann= 5 ,-1 , 0
       0     .12       0  137.46    .045       0   154.9     .12       0
  172.76     .08       0  200.18     .12       0
Bank Sta=137.46,154.9
XS Rating Curve= 0 ,0
Exp/Cntr=0.3,0.1

Type RM Length L Ch R = 1 ,373.9   ,76.8,79.9,81
XS GIS Cut Line= 2
     1795872.002      206588.034     1796168.356       206635.26
#Sta/Elev= 24
       0 1388.22    48.4 1384.99    58.1 1384.17    67.8 1383.13    77.4 1381.75
    87.1 1379.69    96.8 1377.08   106.5 1374.82   116.2 1373.24   125.8    1372
   135.5  1371.3   145.2 1372.27   154.9 1375.69   164.6 1380.24   174.2 1383.75
   183.9 1385.92   193.6 1387.35   203.3 1388.11     213 1388.41  222.651388.398
     242 1387.68   251.7 1387.45     271 1387.07   300.1 1386.72
#Mann= 4 ,-1 , 0
       0     .12       0   125.8    .045       0   145.2     .12       0
  222.65     .06       0
Bank Sta=125.8,145.2
XS Rating Curve= 0 ,0
Exp/Cntr=0.3,0.1

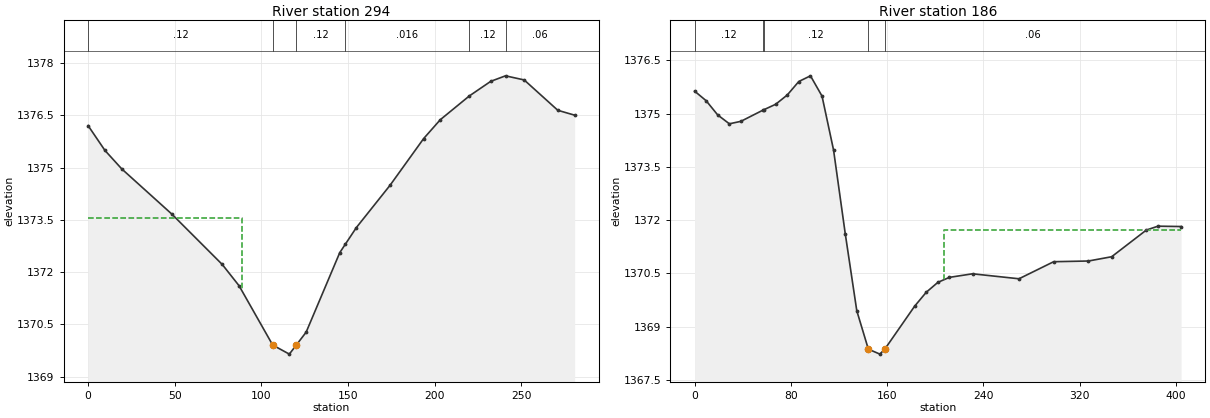
Type RM Length L Ch R = 1 ,294     ,112.6,108.1,103.9
XS GIS Cut Line= 2
     1795858.443      206648.565     1796129.579      206721.078
#Sta/Elev= 22
       0  1376.2     9.7 1375.49    19.4 1374.96    48.4 1373.66    77.4 1372.22
    87.1 1371.61   106.5 1369.91   116.1 1369.65  120.231369.918   125.8 1370.28
   145.2 1372.56  148.371372.798   154.8 1373.28   174.2 1374.49   193.6 1375.83
   203.2 1376.37  219.971377.052   232.3 1377.47  240.821377.628   251.6 1377.51
     271 1376.64   280.7  1376.5
#Mann= 6 ,-1 , 0
       0     .12       0   106.5    .045       0  120.23     .12       0
  148.37    .016       0  219.97     .12       0  240.82     .06       0
#XS Ineff= 2 , 0
           88.85 1373.54
Permanent Ineff=
       F       F
Bank Sta=106.5,120.23
XS Rating Curve= 0 ,0
Exp/Cntr=0.3,0.1

Type RM Length L Ch R = 1 ,186     ,189.4,186,182.1
XS GIS Cut Line= 2
      1795770.83      206765.293     1796174.476       206788.73
#Sta/Elev= 30
       0 1375.63     9.6 1375.36    19.2 1374.96    28.9 1374.71    38.5 1374.78
   57.14  1375.1   57.631375.107    67.4 1375.26      77 1375.52    86.6  1375.9
    96.3 1376.06   105.9 1375.49   115.5 1373.97   125.2 1371.62   134.8 1369.45
   144.4 1368.37     154 1368.23  158.361368.384   182.9 1369.58   192.5 1369.97
   202.2 1370.25   211.8 1370.39     231 1370.49   269.6 1370.35   298.4 1370.83
   327.3 1370.85   346.6 1370.97   375.4 1371.72   385.1 1371.83   404.3 1371.82
#Mann= 5 ,-1 , 0
       0     .12       0   57.14     .06       0   57.63     .12       0
   144.4    .045       0  158.36     .06       0
#XS Ineff= 2 , 0
                          207.43         1371.72
Permanent Ineff=
       F       F
Bank Sta=144.4,158.36
XS Rating Curve= 0 ,0
Exp/Cntr=0.3,0.1

Chan Stop Cuts=-1
Use User Specified Reach Order=0
Composite Channel Slope=5